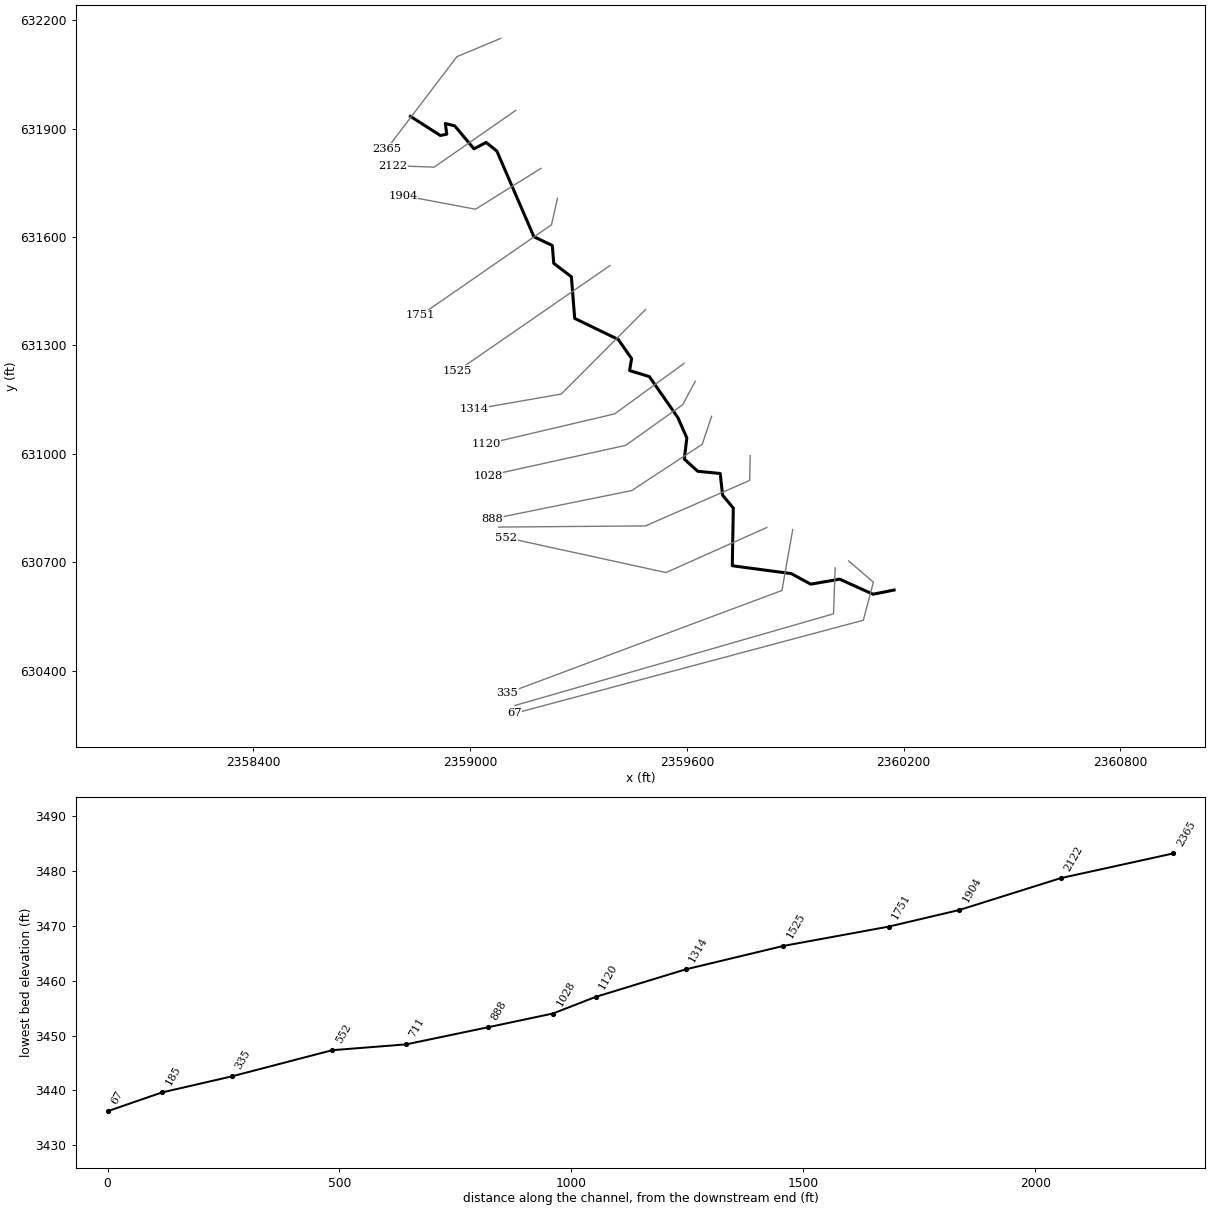
--- GNDYCK.prj (project) ---

Proj Title=GNDYCK
Current Plan=p01
Default Exp/Contr=0,0
English Units
Geom File=g01
Flow File=f01
Plan File=p01
BEGIN DESCRIPTION:
----------MODEL BY WOOD PLC 2022----------
AFH study
Randolph County, WV
HEC-RAS Version: RAS 6.2
Vertical Datum: NAVD88
Projection: NAD 1983 StatePlane West Virginia S FIPS 4702 (US Feet)
Terrain: 1-meter LIDAR (FEMA Region III 3DEP collected 2016-2018)
Land Use: 2019 NLCD
Hydrologic Method:
WV SIR2010-5033 regression equations
Additional Model Notes:
None
END DESCRIPTION:
DSS Export Rating Curves= 0
DSS Export Rating Curve Sorted= 0
DSS Export Volume Flow Curves= 0
DXF OffsetX= 0
DXF OffsetY= 0
DXF ScaleX= 0
DXF ScaleY= 0

--- GNDYCK.p01 (plan) ---

Plan Title=Floodplain
Program Version=6.20
Short Identifier=Floodplain
Geom File=g01
Flow File=f01
Subcritical Flow
K Sum by GR= 0
Std Step Tol= 0.01
Critical Tol= 0.01
Num of Std Step Trials= 20
Max Error Tol= 0.3
Flow Tol Ratio= 0.001
Split Flow NTrial= 30
Split Flow Tol= 0.02
Split Flow Ratio= 0.02
Log Output Level= 0
Friction Slope Method= 1
Unsteady Friction Slope Method= 2
Unsteady Bridges Friction Slope Method= 1
Parabolic Critical Depth
Global Vel Dist= 0 , 0 , 0
Global Log Level= 0
CheckData=True
Encroach Param=-1 ,0,0, 0
Mapping Interval=1HOUR
Computation Time Step Use Courant=        0
Computation Time Step Use Time Series=    0
Computation Time Step Count To Double=0
Computation Time Step Max Doubling=0
Computation Time Step Max Halving=0
Computation Time Step Residence Courant=0
Run HTab= 0
Run UNet= 0
Run Sediment= 0
Run PostProcess= 0
Run WQNet= 0
Run RASMapper=-1
UNET Theta= 0
UNET Theta Warmup= 0
UNET ZTol= 0
UNET ZSATol= 0
UNET MxIter= 0
UNET Max Iter WO Improvement= 0
UNET MaxInSteps= 0
UNET DtIC= 0
UNET DtMin= 0
UNET MaxCRTS= 0
UNET WFStab= 0
UNET SFStab= 0
UNET WFX= 1
UNET SFX= 1
UNET Gravity=32.174
UNET 1D Methodology=Finite Difference
UNET DSS MLevel= 1
UNET Pardiso=0
UNET DZMax Abort= 0
UNET Use Existing IB Tables= 0
UNET Froude Reduction=False
UNET Froude Limit= 0
UNET Froude Power= 0
UNET D1 Cores= 0
UNET WindReference=Eulerian
UNET WindDragFormulation=Hsu (1988)
UNET D2 Coriolis=0
UNET D2 Cores= 0
UNET D2 Theta= 1
UNET D2 Theta Warmup= 1
UNET D2 Z Tol= 0.01
UNET D2 Volume Tol= 0.01
UNET D2 Max Iterations= 20
UNET D2 Equation= 0
UNET D2 RampUpFraction=0.1
UNET D2 TimeSlices= 1
UNET D2 Turbulence Formulation=Non-Conservative (original)
UNET D2 Eddy Viscosity=0.3
UNET D2 Transverse Eddy Viscosity=0.1
UNET D2 Smagorinsky Mixing=0
UNET D2 BCVolumeCheck=0
UNET D2 Cores=0
UNET D2 SolverType=PARDISO (Direct)
UNET D2 Minimum Iterations= 2147483647
UNET D2 Maximum Iterations= 2147483647
UNET D2 Restart Number= 10
UNET D2 Relaxation Coeff=1.3
UNET D2 SOR Precondition Iterations= 10
UNET D2 ILUT Maximum Fill= 8
UNET D2 ILUT Tolerance=1E-08
UNET D1D2 MaxIter= 0
UNET D1D2 ZTol=0.01
UNET D1D2 QTol=0.1
UNET D1D2 MinQTol=1
Write IC File= 0
Write IC File at Fixed DateTime=0
Write IC File at Sim End=0
Echo Input=False
Echo Parameters=False
Echo Output=False
Write Detailed= 0
HDF Write Warmup=0
HDF Write Time Slices=0
HDF Flush=0
HDF Compression= 1
HDF Chunk Size= 1
HDF Spatial Parts= 1
HDF Use Max Rows=0
HDF Fixed Rows= 1
Calibration Method= 0
Calibration Iterations= 20
Calibration Max Change=0.05
Calibration Tolerance=0.2
Calibration Maximum=1.5
Calibration Minimum=0.5
Calibration Optimization Method= 1
WQ AD Non Conservative
WQ ULTIMATE=-1
WQ Max Comp Step=1HOUR
WQ Output Interval=15MIN
WQ Output Selected Increments= 0
WQ Output face flow=0
WQ Output face velocity=0
WQ Output face area=0
WQ Output face dispersion=0
WQ Output cell volume=0
WQ Output cell surface area=0
WQ Output cell continuity=0
WQ Output cumulative cell continuity=0
WQ Output face conc=0
WQ Output face dconc_dx=0
WQ Output face courant=0
WQ Output face peclet=0
WQ Output face adv mass=0
WQ Output face disp mass=0
WQ Output cell mass=0
WQ Output cell source sink temp=0
WQ Output nsm pathways=0
WQ Output nsm derived pathways=0
WQ Create Restart=0
WQ Fixed Restart=0
WQ System Summary=0
WQ Write To DSS=0
Sorting and Armoring Iterations= 10
XS Update Threshold= 0.02
Bed Roughness Predictor= 0
Hydraulics Update Threshold= 0.02
Energy Slope Method= 1
Volume Change Method= 1
Sediment Retention Method= 0
Sediment TS Multiplier= 1
Warm Up Method= 0
XS Weighting Method= 0
Number of US Weighted Cross Sections= 1
Number of DS Weighted Cross Sections= 1
Upstream XS Weight=0
Main XS Weight=1
Downstream XS Weight=0
Number of DS XS's Weighted with US Boundary= 1
Upstream Boundary Weight= 1
Weight of XSs Associated with US Boundary= 0
Number of US XS's Weighted with DS Boundary= 1
Downstream Boundary Weight= 0.5
Weight of XSs Associated with DS Boundary= 0.5
Percentile Method= 0
Sediment Output Level= 3
Mass or Volume Output= 0
Output Increment Type= 1
Profile and TS Output Increment= 1
Transport Output Increment 1
XS Output Flag= 0
XS Output Increment= 10
Read HDF5 Sediment Hotstart= 0
Sediment Hotstart Type= 0
Write Gradation File= 0
Read Gradation Hotstart= 0
Write HDF5 File= 1
Write Binary Output= 1
Write DSS Sediment File= 0
DSS Sediment Output Type= 1
SV Curve= 0
Specific Gage Flag= 0
Subcell Erosion Methods= 0
Subcell Deposition Methods= 0
Advection Scheme= 1
Matrix Solver= 0
Implicit Weighting Factor= 1
Maximum Outer Loop Convergence Iterations= 5
Convergence Maximum Absolute= 0.001
Convergence RMSE= 0.0001
Grain Fractions Max Abs Error= 0.001
Max Subgrid Regions= 1
Max Subgrid Length Scale= 3.402823E+38
Initial Layer Thickness= 3.402823E+38
Min Layer Thickness= 3.402823E+38
Max Layer Thickness= 3.402823E+38
Number of Layers= 5

--- GNDYCK.f01 (steady flow) ---

Flow Title=Flow
Program Version=6.20
Number of Profiles= 1
Profile Names=P100yr
River Rch & RM=GNDYCK,Main,2365
     245
Boundary for River Rch & Prof#=GNDYCK,Main            , 1
Up Type= 0
Dn Type= 3
Dn Slope=0.02935
DSS Import GetInterval= 0
DSS Import GetPeak= 0
DSS Import FillOption= 0

--- GNDYCK.g01 (geometry) ---

Geom Title=Geometry
Program Version=6.20

River Reach=GNDYCK          ,Main
Reach XY= 30
     2358834.738      631934.338     2358917.318      631881.484
     2358935.178      631884.959     2358931.202      631914.705
     2358957.297      631908.019     2359010.535      631844.462
     2359044.189      631862.235     2359073.836      631838.347
     2359176.473      631601.174     2359227.544      631576.713
     2359231.353      631527.493     2359280.268      631490.273
     2359289.397      631374.9882359410.11063514631316.585101478
     2359447.032      631263.677     2359441.413      631230.456
      2359496.12      631213.929     2359575.123      631100.218
     2359599.883      631044.177     2359592.972       630985.35
      2359630.16      630951.633     2359692.304      630945.518
     2359698.915      630885.522     2359728.621      630849.846
 2359725.8165564  630690.0710098      2359889.25      630668.254
      2359943.03      630639.104     2360023.216       630652.92
 2360115.6781887   630611.192906     2360173.766      630622.835

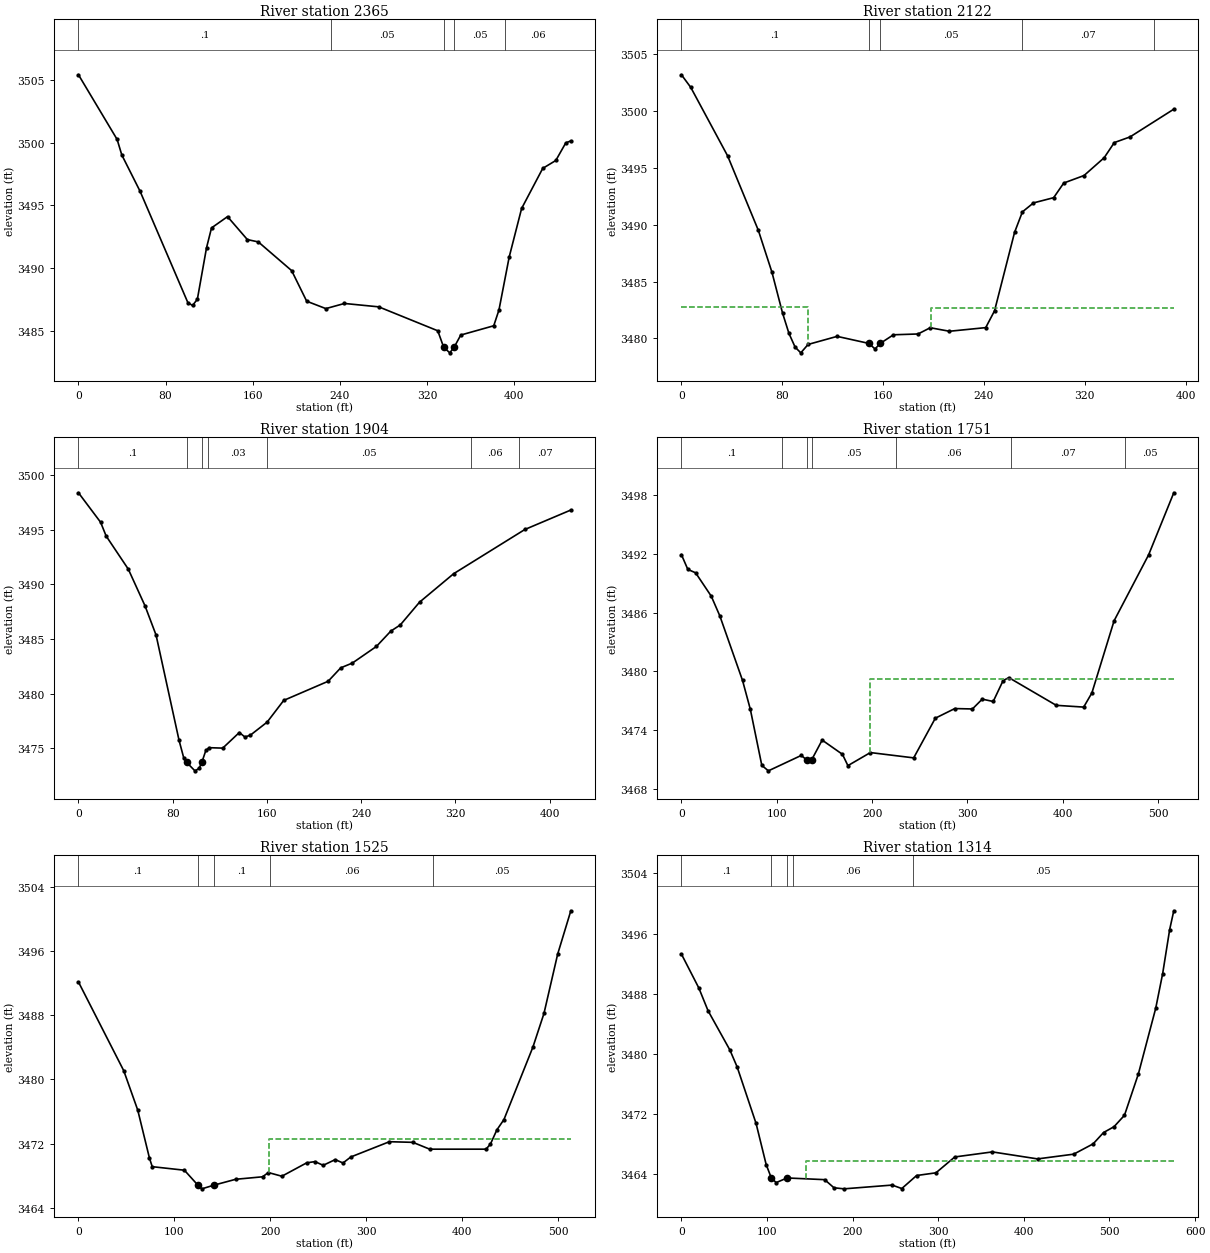
Type RM Length L Ch R = 1 ,2365    ,239.6,243.5,238.2
XS GIS Cut Line= 3
2359084.94307826632150.4711533812358963.22900622632099.699791694
2358769.38822543631844.634887189
#Sta/Elev= 30
       0 3505.43    35.5 3500.27    39.8 3499.03    56.6 3496.13   100.5 3487.24
   104.8 3487.02   109.2 3487.52   117.6 3491.62   122.2 3493.21   136.9 3494.11
   155.1 3492.28   165.2 3492.09   195.8  3489.8   209.6 3487.36   227.2 3486.77
   244.3 3487.18   275.8 3486.91     330    3485  335.36  3483.7     341 3483.24
  345.12  3483.7   351.1 3484.66   381.4  3485.4   386.2 3486.66   395.6 3490.89
     407 3494.76   426.4 3497.96   438.4 3498.59   447.6    3500   452.2 3500.15
#Mann= 5 ,-1,0
       0      .1       0  231.88     .05       0  335.36    .045       0
  345.12     .05       0  391.88     .06       0
Bank Sta=335.36,345.12
XS Rating Curve= 0 ,0
Exp/Cntr(USF)=0,0
Exp/Cntr=0.3,0.1

Type RM Length L Ch R = 1 ,2122    ,213.4,217.8,212.9
XS GIS Cut Line= 3
2359126.24341425 631950.98482897  2358900.282703631793.853083182
2358784.96737011 631797.89862679
#Sta/Elev= 30
       0  3503.2     7.4 3502.09    36.6 3496.07      61 3489.51    71.8 3485.82
    80.2 3482.23    85.3 3480.43    90.2 3479.22    94.7 3478.72   100.5 3479.46
   123.5 3480.17   148.7 3479.55   153.6 3479.06  157.72 3479.55   168.2 3480.31
   187.7 3480.38   197.4 3480.93   212.6 3480.62   241.4 3480.94   248.4 3482.42
   264.3 3489.33   270.5 3491.13   279.3 3491.92   295.3 3492.38   303.3 3493.67
   319.4 3494.33   335.4  3495.9   343.4 3497.23   355.9 3497.73   390.6 3500.17
#Mann= 5 ,-1,0
       0      .1       0   148.7    .045       0  157.72     .05       0
     270     .07       0  375.22     .06       0
#XS Ineff= 2 , 0
          100.38 3482.75  198.22         3482.63
Permanent Ineff=
       F       F
Bank Sta=148.7,157.72
XS Rating Curve= 0 ,0
Exp/Cntr(USF)=0,0
Exp/Cntr=0.3,0.1

Type RM Length L Ch R = 1 ,1904    ,153,152.7,152.3
XS GIS Cut Line= 3
2359196.09586983631790.3771471282359014.70903833631677.291100264
2358813.85364257631715.137308896
#Sta/Elev= 30
       0 3498.38    18.8 3495.68    23.5 3494.42    42.3 3491.39    56.5 3488.03
    65.9 3485.35    85.4 3475.72    89.5 3474.06   91.923473.687    98.9 3472.92
   102.4 3473.14  104.733473.689   108.2  3474.8   111.1 3475.04   122.5    3475
   136.6 3476.43   141.3 3476.02   145.9 3476.18   160.2 3477.38   174.3 3479.37
     212 3481.12   222.7 3482.35   232.6 3482.79     253 3484.31   265.2 3485.71
   273.3 3486.28   289.6 3488.36   318.6 3490.97   379.1 3495.02   418.1  3496.8
#Mann= 7 ,-1,0
       0      .1       0   91.92    .045       0  104.73      .1       0
     110     .03       0     160     .05       0  333.75     .06       0
  373.75     .07       0
Bank Sta=91.92,104.73
XS Rating Curve= 0 ,0
Exp/Cntr(USF)=0,0
Exp/Cntr=0.3,0.1

Type RM Length L Ch R = 1 ,1751    ,224.1,226.8,219.6
XS GIS Cut Line= 3
2359241.84264597631707.7377792072359225.25936938631634.291384767
2358862.51678601631383.370356826
#Sta/Elev= 30
       0 3491.89     6.7 3490.39    14.9 3490.04    31.3 3487.66    40.3 3485.65
    64.1 3479.08    72.3 3476.13    84.3 3470.44    91.2 3469.88   125.7 3471.45
   131.5 3470.98  136.48 3470.98   147.6 3473.01   168.9 3471.56   174.6 3470.41
   198.2 3471.74   243.6  3471.2   266.3 3475.24   286.7 3476.22   305.2 3476.18
   315.5 3477.18     327 3476.94   337.4 3479.07   343.4 3479.37   393.1 3476.55
   421.9 3476.37   430.5 3477.81   453.8 3485.16     490 3491.87   516.4 3498.19
#Mann= 7 ,-1,0
       0      .1       0   105.3     .05       0   131.5    .045       0
  136.48     .05       0   225.3     .06       0   345.3     .07       0
   465.3     .05       0
#XS Ineff= 2 , 0
                          198.08         3479.25
Permanent Ineff=
       F       F
Bank Sta=131.5,136.48
XS Rating Curve= 0 ,0
Exp/Cntr(USF)=0,0
Exp/Cntr=0.3,0.1

Type RM Length L Ch R = 1 ,1525    ,209.4,211.2,210
XS GIS Cut Line= 2
 2359387.0205131631521.2543296172358964.73449021631229.535607321
#Sta/Elev= 30
       0 3492.12    47.2 3481.07    61.8 3476.16      74 3470.18    76.9 3469.12
   110.4 3468.68  124.55 3466.81   128.6 3466.36   140.9 3466.81   163.9 3467.55
   191.9 3467.86   197.9 3468.39     212 3467.93   237.9  3469.6   246.5 3469.75
   255.1 3469.29   267.6    3470   275.7 3469.58   283.9 3470.33   324.1 3472.23
   348.6 3472.15   366.1  3471.3   424.8  3471.3   429.4 3471.93   436.1  3473.7
   443.5 3474.99   473.7 3484.02   485.2  3488.2   499.5  3495.6   513.2 3500.99
#Mann= 5 ,-1,0
       0      .1       0  124.55    .045       0   140.9      .1       0
     200     .06       0     370     .05       0
#XS Ineff= 2 , 0
                          198.08         3472.59
Permanent Ineff=
       F       F
Bank Sta=124.55,140.9
XS Rating Curve= 0 ,0
Exp/Cntr(USF)=0,0
Exp/Cntr=0.3,0.1

Type RM Length L Ch R = 1 ,1314    ,192,194,187.6
XS GIS Cut Line= 3
2359485.80457591631399.5528907532359252.09129781631165.466370292
2359011.42124047631123.549790049
#Sta/Elev= 30
       0 3493.28    20.3 3488.78    31.1 3485.75    56.6 3480.53    65.1 3478.27
    87.2 3470.76      99 3465.29     1053463.515   110.7  3462.9   123.43463.517
   167.3 3463.29   178.2 3462.21   189.9 3462.07   246.1 3462.57   257.4 3462.11
   274.7 3463.84   297.3  3464.2   319.3 3466.31   363.2 3466.98     416 3466.05
   458.2 3466.68   480.9 3468.05   493.1 3469.56   505.3 3470.33   517.5 3471.85
   533.7 3477.33     554 3486.08   562.1 3490.68   570.3 3496.55   575.1 3499.04
#Mann= 5 ,-1,0
       0      .1       0     105    .045       0   123.4      .1       0
     130     .06       0     270     .05       0
#XS Ineff= 2 , 0
                          145.28         3465.79
Permanent Ineff=
       F       F
Bank Sta=105,123.4
XS Rating Curve= 0 ,0
Exp/Cntr(USF)=0,0
Exp/Cntr=0.3,0.1

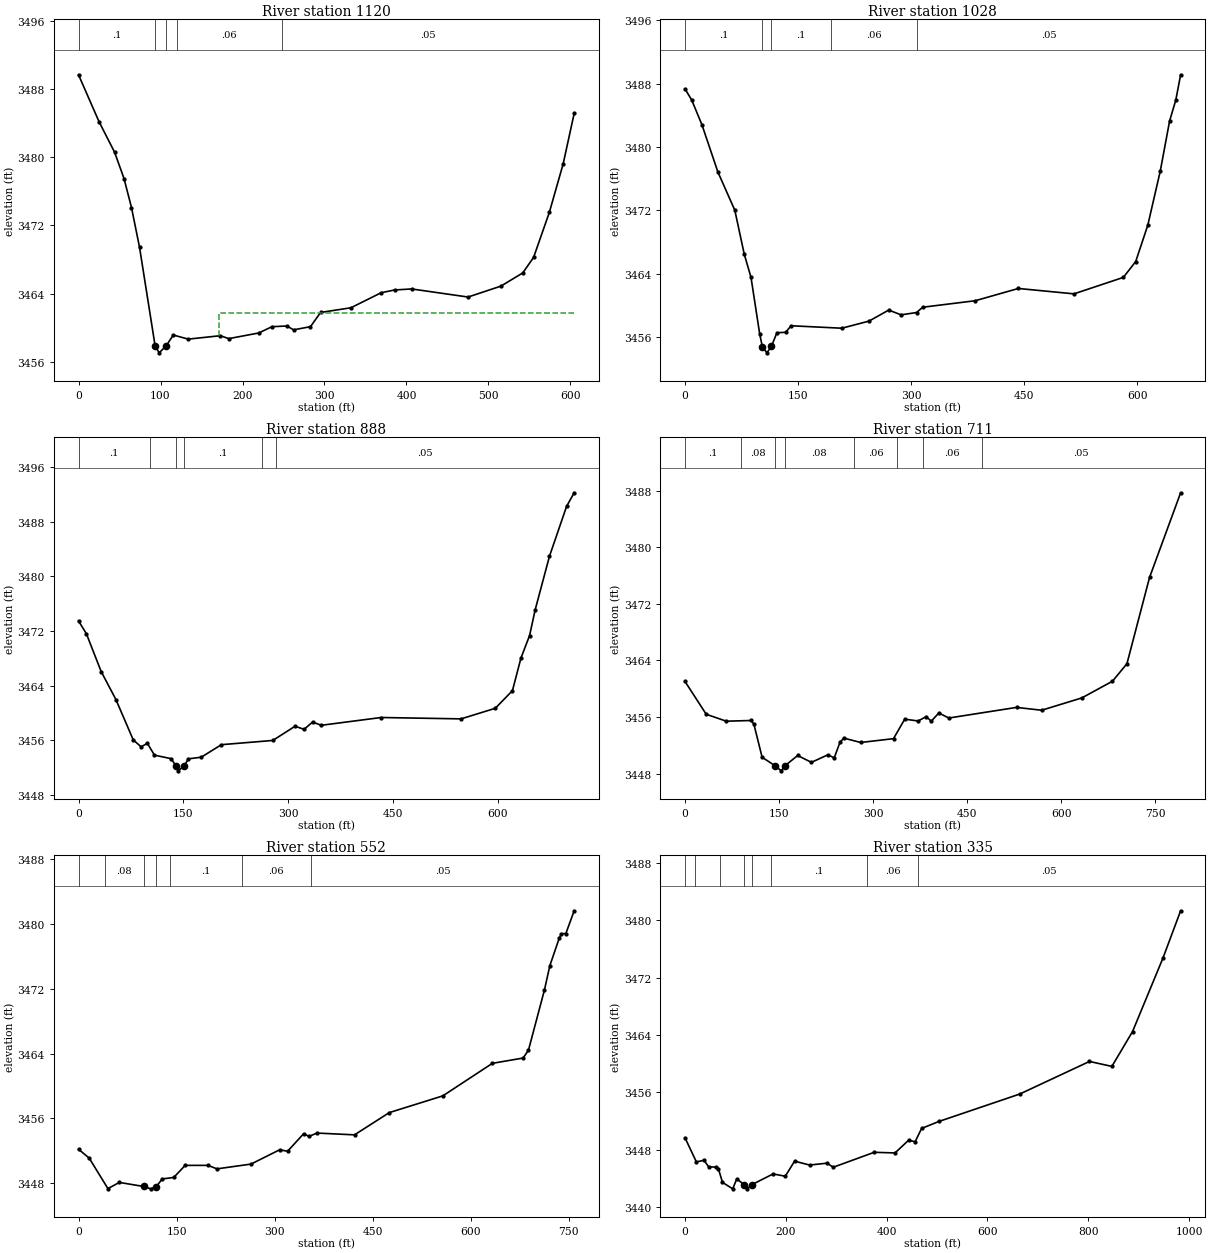
Type RM Length L Ch R = 1 ,1120    ,91.9,92,91.5
XS GIS Cut Line= 3
2359592.37581217631250.4887279642359400.15610112631110.632211448
2359043.14251724631026.712647587
#Sta/Elev= 30
       0 3489.69      25 3484.19      44  3480.6    55.5 3477.51    64.6 3474.11
    74.4 3469.45    93.43457.887    98.4 3457.05     107 3457.89   115.6 3459.14
   133.8 3458.66   172.9 3459.06   183.3 3458.72   219.8 3459.38   235.9 3460.12
   254.1  3460.2   262.3 3459.75   282.9 3460.12   295.2 3461.79   332.2 3462.34
   369.2 3464.11   385.6 3464.43   406.2 3464.55   475.1  3463.6   515.1 3464.88
   541.8 3466.43     555 3468.25   574.2 3473.53   591.1 3479.24   604.5 3485.15
#Mann= 5 ,-1,0
       0      .1       0    93.4    .045       0     107      .1       0
     120     .06       0  247.71     .05       0
#XS Ineff= 2 , 0
                          170.94         3461.68
Permanent Ineff=
       F       F
Bank Sta=93.4,107
XS Rating Curve= 0 ,0
Exp/Cntr(USF)=0,0
Exp/Cntr=0.3,0.1

Type RM Length L Ch R = 1 ,1028    ,139.1,140.1,139
XS GIS Cut Line= 4
2359623.38950154631201.1307727532359588.51820309 631135.98241725
2359430.48341733631023.3977698962359049.98384487 630939.44557767
#Sta/Elev= 30
       0 3487.36       9 3485.94    22.6  3482.8    43.7 3476.85    66.1 3472.04
    78.7 3466.46    87.6 3463.55    99.1 3456.42  102.61 3454.81   108.7 3454.02
   114.6 3454.83     122 3456.56   133.5 3456.61   140.8 3457.44   208.1 3457.13
   244.2 3458.03   270.3 3459.42   286.7 3458.82   307.2 3459.11   315.4 3459.78
     385  3460.6   442.3 3462.15   516.1 3461.47   581.6 3463.55     598 3465.55
     614 3470.13   630.7 3477.03     643 3483.32   651.2 3485.95   657.6 3489.14
#Mann= 5 ,-1,0
       0      .1       0  102.61    .045       0   114.6      .1       0
  193.89     .06       0  307.93     .05       0
Bank Sta=102.61,114.6
XS Rating Curve= 0 ,0
Exp/Cntr(USF)=0,0
Exp/Cntr=0.3,0.1

Type RM Length L Ch R = 1 ,888     ,177.1,176.4,173.3
XS GIS Cut Line= 4
2359668.53633393631103.9261756112359642.54236003631026.287925696
2359447.17300668630898.2258497842359061.58502401630819.901364427
#Sta/Elev= 30
       0 3473.47    11.3 3471.58    32.4 3466.05    53.5 3461.95    78.3 3456.04
    89.5 3455.03    98.5 3455.54   108.6 3453.81   132.5 3453.29  139.62 3452.19
   142.3 3451.51   151.23452.213   156.9 3453.26   175.6 3453.51   204.3 3455.34
   277.9 3455.96   309.7 3458.04   322.6 3457.59   334.9 3458.66   347.1 3458.18
   432.8 3459.32   547.1 3459.12   596.1 3460.67   620.6 3463.25   632.8 3468.03
   645.1 3471.31   653.2 3475.12   673.6 3482.94   698.1 3490.25   708.9 3492.23
#Mann= 6 ,-1,0
       0      .1       0  101.87     .08       0  139.62    .045       0
   151.2      .1       0  261.87     .06       0  281.87     .05       0
Bank Sta=139.62,151.2
XS Rating Curve= 0 ,0
Exp/Cntr(USF)=0,0
Exp/Cntr=0.3,0.1

Type RM Length L Ch R = 1 ,711     ,156,159.1,158
XS GIS Cut Line= 4
2359775.45467332630995.0331104112359773.87461178 630926.30246655
2359485.24022409 630800.374654392359078.56347127630797.191958338
#Sta/Elev= 30
       0 3461.03    33.9 3456.39    65.9 3455.41   105.5 3455.51   109.9 3454.98
     123 3450.31   143.8  3449.1   153.5 3448.39  159.34  3449.1   179.7 3450.56
   201.6 3449.59   227.7 3450.65     238 3450.23   247.1 3452.42   253.2 3453.02
   280.1  3452.4   332.5 3452.94   350.4  3455.7   371.8 3455.44   384.7 3456.06
   392.7 3455.41   404.7 3456.57   420.7 3455.86   528.7 3457.36   568.7 3456.96
   632.7  3458.7   681.6 3461.06   704.7 3463.54   740.7 3475.73   790.3 3487.71
#Mann= 8 ,-1,0
       0      .1       0   88.75     .08       0   143.8    .045       0
  159.34     .08       0  268.75     .06       0  338.75      .1       0
  378.75     .06       0  473.66     .05       0
Bank Sta=143.8,159.34
XS Rating Curve= 0 ,0
Exp/Cntr(USF)=0,0
Exp/Cntr=0.3,0.1

Type RM Length L Ch R = 1 ,552     ,206.5,217.1,222.1
XS GIS Cut Line= 3
2359821.21913176630795.8468054142359542.30366597630671.247434647
2359099.81441768630767.879818787
#Sta/Elev= 30
       0 3452.21    16.3 3451.12      45 3447.36    62.5 3448.12    99.7 3447.62
   110.7 3447.33  118.89 3447.61   128.2 3448.55   145.7 3448.73   163.2 3450.22
   198.3 3450.22   211.8 3449.79     264 3450.38   307.7 3452.14   319.9 3451.96
   344.5 3454.12   352.6 3453.79     365  3454.2   422.3 3453.98   475.5 3456.72
   557.4 3458.78   633.3 3462.79   680.2 3463.44   688.4 3464.39     713 3471.85
   721.2 3474.82   735.7 3478.24     739 3478.75   745.7 3478.78   758.4 3481.58
#Mann= 7 ,-1,0
       0     .03       0      40     .08       0    99.7    .045       0
  118.89     .08       0     140      .1       0     250     .06       0
  355.48     .05       0
Bank Sta=99.7,118.89
XS Rating Curve= 0 ,0
Exp/Cntr(USF)=0,0
Exp/Cntr=0.3,0.1

Type RM Length L Ch R = 1 ,335     ,149,150.1,149.8
XS GIS Cut Line= 3
2359893.19611405630790.4145305242359863.24518094630621.627144412
 2359102.8334517 630337.39974172
#Sta/Elev= 30
       0 3449.67    22.6  3446.3    37.8 3446.53    46.8 3445.62    62.2 3445.57
    66.3 3445.35    74.4 3443.44    94.7 3442.54   102.8 3443.94  117.02 3443.12
   123.1 3442.56   132.73443.121   174.7 3444.62     199  3444.3   217.4  3446.4
   247.3 3445.86   281.5 3446.12   294.3 3445.56   375.4 3447.64   416.6 3447.55
   443.7 3449.33   456.5 3449.11   469.4 3450.97   503.5 3451.94     664 3455.77
   802.4 3460.32   846.8 3459.63   887.8 3464.49   948.2 3474.76   983.2 3481.35
#Mann= 8 ,-1,0
       0      .1       0      20     .03       0      70     .08       0
  117.02    .045       0   132.7     .08       0     170      .1       0
  361.42     .06       0  461.42     .05       0
Bank Sta=117.02,132.7
XS Rating Curve= 0 ,0
Exp/Cntr(USF)=0,0
Exp/Cntr=0.3,0.1

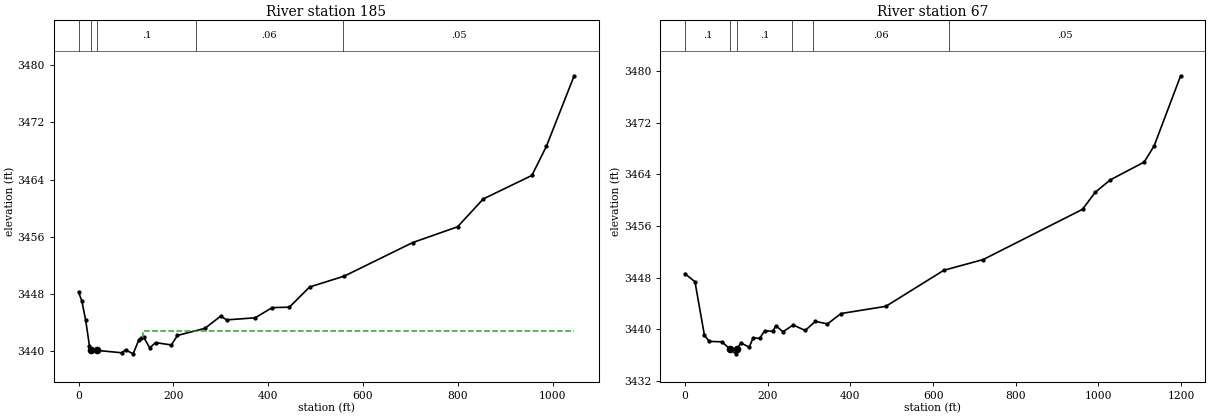
Type RM Length L Ch R = 1 ,185     ,115,117.4,113.5
XS GIS Cut Line= 3
 2360010.7084565630684.2654153012360006.09869447630556.965063686
2359123.92290485630303.080646831
#Sta/Elev= 30
       0 3448.28     7.1 3446.99    15.1 3444.33    23.1 3440.72   27.01  3440.1
    39.1  3440.1    91.1 3439.77    99.2 3440.18   115.2 3439.62   127.2 3441.57
     132 3441.84   137.7 3441.92   150.2 3440.46   162.7 3441.19     196 3440.86
   208.5 3442.19   266.7 3443.19     300  3444.9   312.5 3444.37   372.5 3444.66
   408.3 3446.08   444.8 3446.15   487.5 3448.97   560.5 3450.49   705.1 3455.19
   799.5 3457.39   853.6 3461.28   956.2 3464.57   986.8 3468.64  1045.4 3478.51
#Mann= 5 ,-1,0
       0      .1       0   27.01    .045       0    39.1      .1       0
  247.38     .06       0  557.38     .05       0
#XS Ineff= 2 , 0
                             135         3442.87
Permanent Ineff=
       F       F
Bank Sta=27.01,39.1
XS Rating Curve= 0 ,0
Exp/Cntr(USF)=0,0
Exp/Cntr=0.3,0.1

Type RM Length L Ch R = 1 ,67      ,,,
XS GIS Cut Line= 4
2360048.16820066630703.3205395892360116.47181192630644.540553669
2360088.61148549630539.1613860022359122.88672756630281.294702812
#Sta/Elev= 30
       0  3448.6    24.2 3447.35    46.9  3439.1    58.5 3438.12    89.1 3438.05
   109.5 3436.91   122.6 3436.19  125.97 3436.91     135 3437.89   155.3 3437.22
   165.1 3438.69   180.5 3438.57   192.9 3439.78     212 3439.67   220.3 3440.54
     237  3439.6   261.7 3440.66   290.6 3439.81   315.5 3441.22   344.5 3440.82
   377.4 3442.43   485.9 3443.55     626 3449.13   721.2 3450.79   961.4 3458.57
   991.9 3461.19  1028.6 3463.13  1110.4 3465.88  1134.6 3468.39  1198.7 3479.25
#Mann= 6 ,-1,0
       0      .1       0   109.5    .045       0  125.97      .1       0
  259.11     .08       0  309.11     .06       0  639.11     .05       0
Bank Sta=109.5,125.97
XS Rating Curve= 0 ,0
Exp/Cntr(USF)=0,0
Exp/Cntr=0.3,0.1
LCMann Table=0

Chan Stop Cuts=-1
Use User Specified Reach Order=0
Composite Channel Slope=5